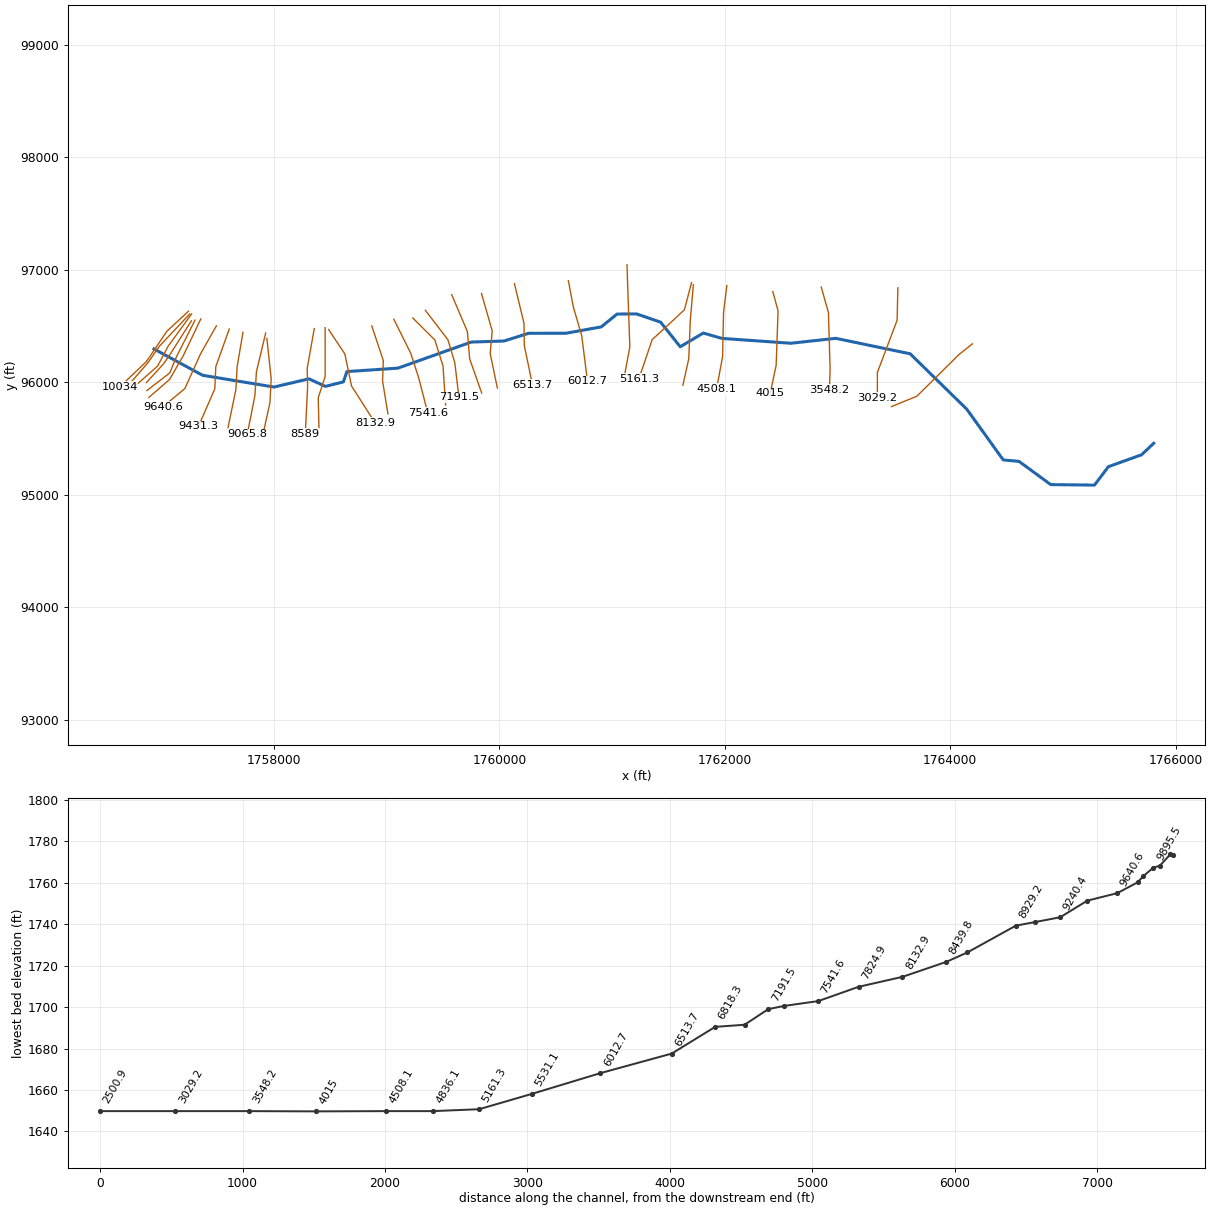
--- Big Branch A.prj (project) ---

Proj Title=Big Branch A
Current Plan=p01
Default Exp/Contr=0,0
English Units
Geom File=g01
Flow File=f01
Plan File=p01
BEGIN DESCRIPTION:
END DESCRIPTION:
DSS Export Rating Curves= 0
DSS Export Rating Curve Sorted= 0
DSS Export Volume Flow Curves= 0
DXF OffsetX= 0
DXF OffsetY= 0
DXF ScaleX= 0
DXF ScaleY= 0

--- Big Branch A.p01 (plan) ---

Plan Title=Floodplain
Program Version=4.00
Geom File=g01
Flow File=f01
K Sum by GR=0
Std Step Tol=0.01
Critical Tol=0.01
Num of Std Step Trials=20
Max Error Tol=0.3
Flow Tol Ratio=0.001
Split Flow NTrial=30
Split Flow Tol=0.02
Split Flow Ratio=0.02
Log Output Level=0
Friction Slope Method=1
Unsteady Friction Slope Method=2
Unsteady Bridges Friction Slope Method=1
Global Log Level=0
CheckData=False
Run HTab=0
Run UNet=0
Run PostProcess=0
UNET Theta=0
UNET Theta Warmup=0
UNET ZTol=0
UNET ZSATol=0
UNET MxIter=0
UNET MaxInSteps=0
UNET DtIC=0
UNET DtMin=0
UNET MaxCRTS=0
UNET WFStab=0
UNET SFStab=0
UNET WFX=0
UNET SFX=0
UNET DSS MLevel=0
UNET DZMax Abort=0
UNET Convert EG Bridges=0
UNET Use Existing IB Tables=0
UNET Froude Limit=0
UNET Froude Power=0
Write IC File=0
Echo Input=False
Echo Output=False
Write Detailed=0

--- Big Branch A.f01 (steady flow) ---

Flow Title=NFF Regression Equation
Program Version=4.00
Number of Profiles=1
Profile Names=P100yr
River Rch & RM=Big Branch A,Main      ,10034
281.5494
River Rch & RM=Big Branch A,Main      ,9640.6
579.8260
River Rch & RM=Big Branch A,Main      ,8439.8
596.8635
River Rch & RM=Big Branch A,Main      ,8132.9
1163.698
River Rch & RM=Big Branch A,Main      ,4836.1
1270.533
River Rch & RM=Big Branch A,Main      ,1840.8
1394.409
River Rch & RM=Big Branch A,Main      ,1338.6
1646.326
Boundary for River Rch & Prof#=Big Branch A,Main      ,1
Up Type=0
Dn Type=3
Dn Slope=0.003763

--- Big Branch A.g01 (geometry) ---

Geom Title=USGS 10m DEM
Program Version=4.00

River Reach=Big Branch A    ,Main
Reach XY= 30
      1756935.69       96295.346     1757368.091       96060.916
     1758001.833        95956.71     1758310.906       96029.725
     1758456.935       95962.381     1758616.434       96002.787
     1758647.625       96094.233     1759100.601       96124.715
     1759750.647        96356.52     1760041.289       96365.735
     1760259.625       96434.497     1760590.143       96434.748
     1760903.291       96491.208     1761044.359       96605.338
     1761217.326       96606.756       1761430.7       96533.032
     1761604.376       96314.696     1761809.243       96436.624
     1761972.996       96389.129     1762586.225       96345.897
     1762983.942       96389.691      1763644.42       96252.054
     1764146.706         95759.6      1764469.79       95308.927
     1764609.667       95296.124     1764891.196       95089.669
     1765279.082         95085.2     1765402.419       95248.756
     1765697.356       95355.112     1765804.605       95456.999

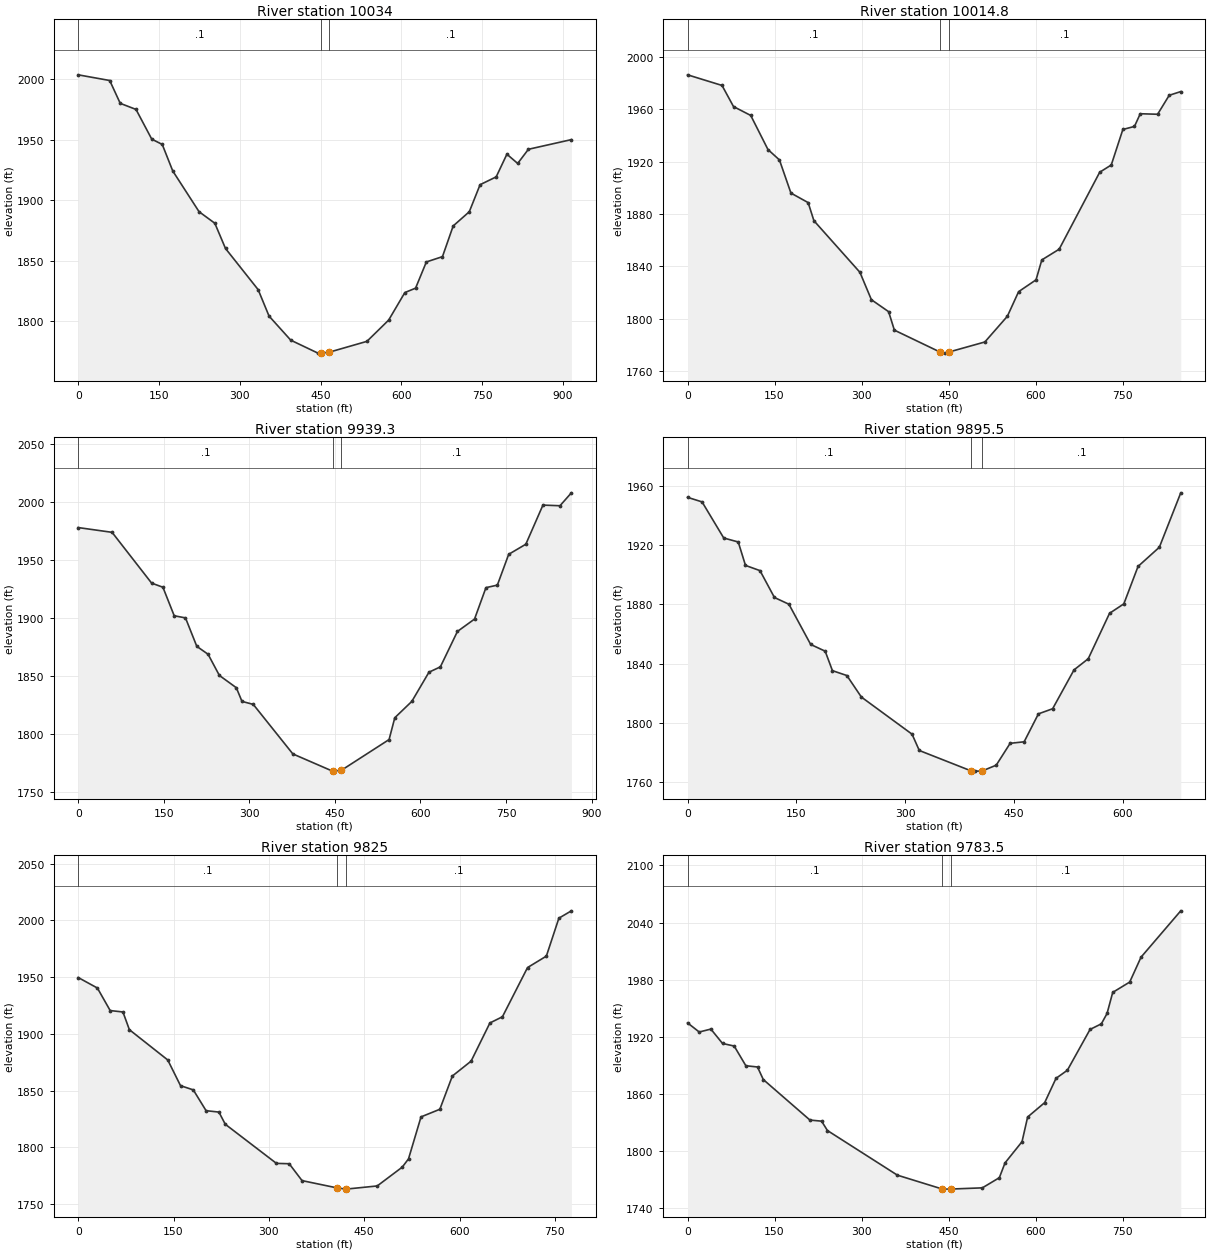
Type RM Length L Ch R = 1 ,10034   ,19.6,19.2,18.8
XS GIS Cut Line= 4
     1757242.881       96631.125     1757050.036       96451.843
     1756869.807       96183.752     1756631.558       95956.857
#Sta/Elev= 30
       0 2003.81    58.5 1999.11      78 1980.23   107.3 1975.19   136.5 1950.63
     156 1946.23   175.5 1924.29   224.3 1890.61   253.6 1881.04   273.4 1860.17
     334 1826.12   354.2 1804.28   394.5 1784.34     445 1773.62   450.7 1773.65
   465.7 1774.37   535.9 1783.36   576.2 1800.93   606.3 1823.72   626.2 1827.36
   646.2 1849.04   676.1 1853.42     696 1878.82   725.9 1890.57   745.9 1912.93
   775.8  1919.4   795.7 1938.16   815.7 1930.51   835.6 1942.22   915.4 1950.22
#Mann= 3 , 0 , 0
       0      .1       0   450.7    .045       0   465.7      .1       0
Bank Sta=450.7,465.7
XS Rating Curve= 0 ,0
Exp/Cntr=0.3,0.1

Type RM Length L Ch R = 1 ,10014.8 ,72.7,75.5,78.4
XS GIS Cut Line= 4
     1757252.794       96605.038     1756988.012       96323.922
     1756882.409       96172.558     1756699.364       95961.352
#Sta/Elev= 30
       0 1986.18    59.4 1978.08    79.2 1961.96   108.9 1955.18   138.6 1929.17
   158.4 1921.22   178.2 1895.94   207.9 1888.65   217.8 1874.86   297.1 1835.49
   316.9 1814.56   346.6 1805.42   356.5 1791.34   435.9 1774.47   444.5 1773.79
   450.9 1774.67   512.5  1782.3   551.3 1801.92   570.7  1820.7   600.7 1829.71
   610.7 1844.93   640.6  1853.1   710.5 1911.86   730.4 1917.37   750.4 1944.48
   770.4  1946.8   780.4 1956.48   810.3 1956.09   830.3 1970.56   850.2 1973.39
#Mann= 3 , 0 , 0
       0      .1       0   435.9    .045       0   450.9      .1       0
Bank Sta=435.9,450.9
XS Rating Curve= 0 ,0
Exp/Cntr=0.3,0.1

Type RM Length L Ch R = 1 ,9939.3  ,46.3,43.8,41.3
XS GIS Cut Line= 4
     1757270.817        96607.29     1757061.301       96318.924
     1756968.933         96143.2     1756736.888        95938.19
#Sta/Elev= 30
       0  1977.8    59.4  1973.7   128.7 1929.99   148.5 1926.45   168.3  1901.9
   188.1 1900.05   207.9 1875.58   227.7 1868.74   247.5 1850.53   277.2 1839.96
   287.1  1828.2   306.9 1825.61   376.3 1782.98   445.8 1768.18   446.2 1768.19
   461.2 1768.85     545 1795.35     555 1814.12   584.9 1828.22   614.9 1853.32
   634.9 1857.91   664.8 1888.39   694.8 1899.05   714.8 1926.09   734.8 1928.27
   754.7 1954.79   784.7 1963.46   814.7 1997.14   844.6 1996.59   864.6  2007.7
#Mann= 3 , 0 , 0
       0      .1       0   446.2    .045       0   461.2      .1       0
Bank Sta=446.2,461.2
XS Rating Curve= 0 ,0
Exp/Cntr=0.3,0.1

Type RM Length L Ch R = 1 ,9895.5  ,65.9,70.5,75
XS GIS Cut Line= 4
     1757268.155       96545.352     1757086.295       96258.573
     1757021.944       96163.446     1756869.462       95996.974
#Sta/Elev= 30
       0 1952.35      20 1949.27    49.9 1924.87    69.9 1922.18    79.9 1906.35
    99.9 1902.82   119.8 1884.68   139.8 1880.11   169.8 1852.95   189.8 1848.39
   199.8 1835.23   219.7 1831.94   239.7  1817.4   309.6 1792.31   319.6 1781.29
   390.8 1767.55     397 1767.34   405.8 1767.35   425.7 1771.36   444.9 1786.13
   464.2 1787.16   483.9 1806.04   503.5  1809.5     533 1835.76   552.6 1843.28
     582 1873.99   601.7 1880.37   621.3 1905.67   650.7 1918.64   680.2  1955.4
#Mann= 3 , 0 , 0
       0      .1       0   390.8    .045       0   405.8      .1       0
Bank Sta=390.8,405.8
XS Rating Curve= 0 ,0
Exp/Cntr=0.3,0.1

Type RM Length L Ch R = 1 ,9825    ,44.3,41.5,38.4
XS GIS Cut Line= 4
      1757300.33       96550.948     1757136.656       96227.796
     1757076.502       96082.308     1756873.658       95925.629
#Sta/Elev= 30
       0 1949.62    30.2 1940.36    50.3 1920.52    70.4 1919.27    80.5 1903.68
   140.9    1877     161 1854.35   181.1 1850.65   201.2 1832.33   221.4  1831.1
   231.4 1820.39   311.9 1785.92     332 1785.61   352.2 1770.74   406.9 1764.36
   421.3 1763.24   421.9 1763.28   470.5 1766.04   509.8 1782.58   519.7 1789.87
   539.4 1826.87     569 1833.57   588.7 1862.86   618.2 1875.98   647.8  1909.6
   667.5 1915.06     707 1958.39   736.6 1968.46   756.3 2001.88     776 2008.36
#Mann= 3 , 0 , 0
       0      .1       0   406.9    .045       0   421.9      .1       0
Bank Sta=406.9,421.9
XS Rating Curve= 0 ,0
Exp/Cntr=0.3,0.1

Type RM Length L Ch R = 1 ,9783.5  ,140.8,142.9,145.2
XS GIS Cut Line= 4
      1757351.92       96562.233     1757196.472       96235.568
     1757074.818       96023.798     1756890.083       95863.845
#Sta/Elev= 30
       0 1934.68    20.1  1925.1    40.2 1928.17    60.3 1913.08    80.4 1910.36
   100.5  1889.7   120.6 1888.38   130.6 1875.19     211 1832.68   231.1 1831.52
   241.2 1821.68   361.8 1774.83   438.6 1760.39   439.9 1760.18   453.6 1760.25
   508.3 1761.52   537.6 1772.18   547.4 1787.72   576.7 1809.96   586.4 1835.89
   615.8    1851   635.3 1876.46   654.9 1884.96     694  1927.8   713.5 1933.69
   723.3 1944.54   733.1 1966.68   762.4 1977.54   781.9 2003.65   850.4  2052.3
#Mann= 3 , 0 , 0
       0      .1       0   438.6    .045       0   453.6      .1       0
Bank Sta=438.6,453.6
XS Rating Curve= 0 ,0
Exp/Cntr=0.3,0.1

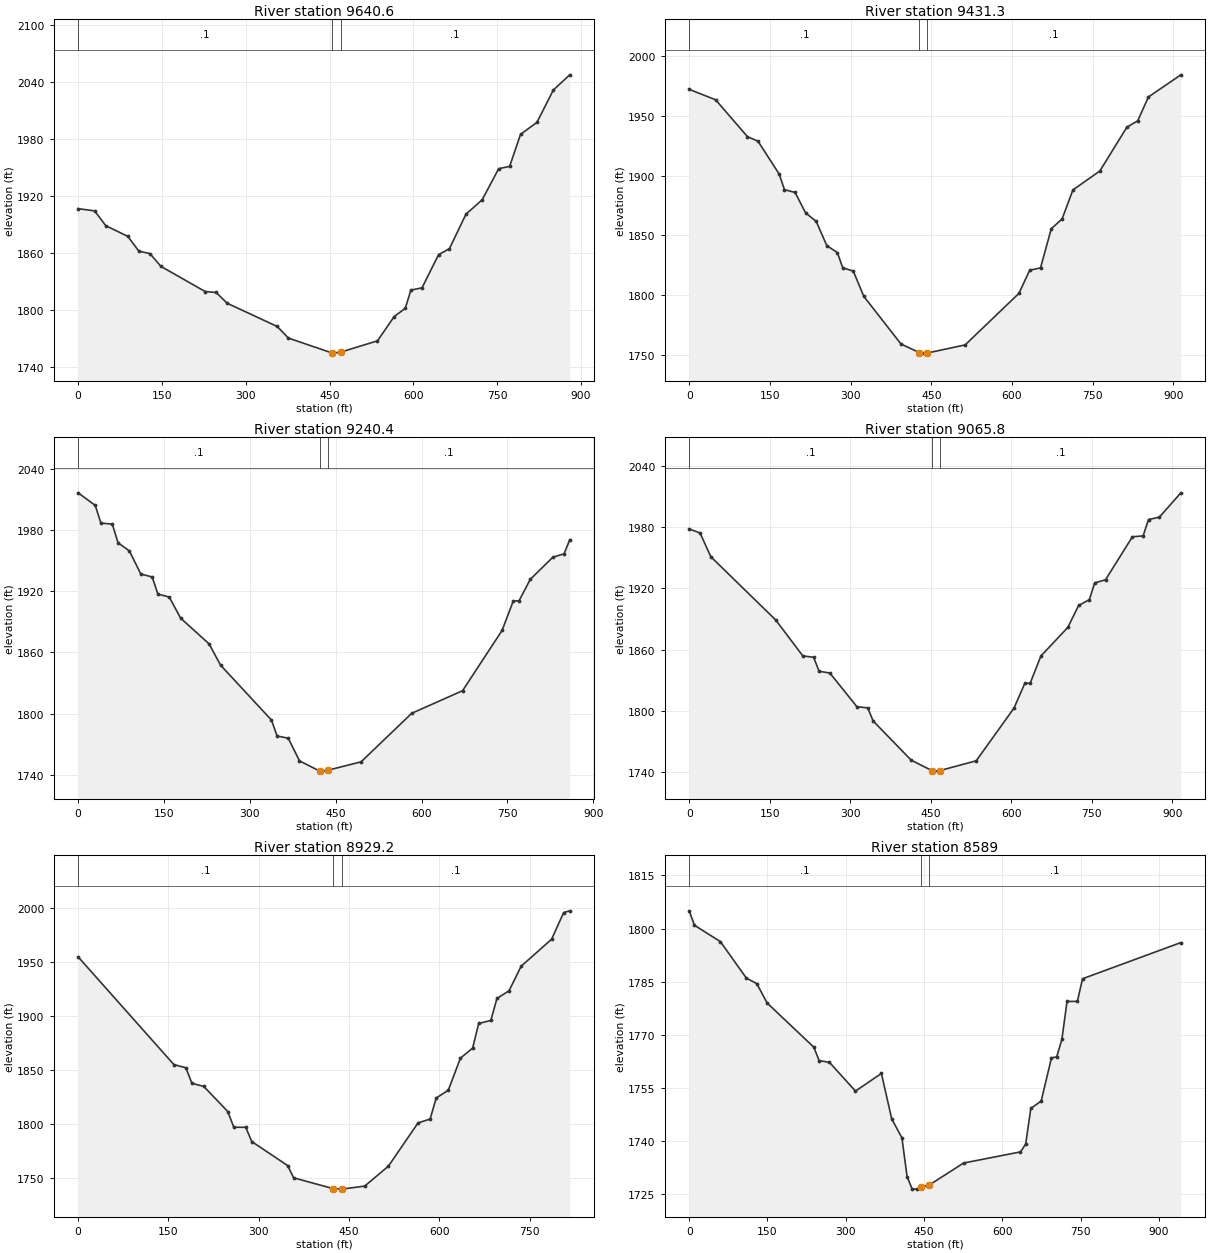
Type RM Length L Ch R = 1 ,9640.6  ,200.7,209.2,217.8
XS GIS Cut Line= 4
      1757490.22       96501.069     1757349.292       96251.578
      1757209.99       95942.695      1757013.99       95780.489
#Sta/Elev= 30
       0 1906.95    29.6  1904.6    49.4 1889.05    88.9 1877.81   108.7 1862.24
   128.4 1859.71   148.2 1846.23   227.3 1819.77     247 1818.75   266.8 1807.42
   356.3 1782.99   376.2 1770.82   454.6 1755.08     456 1754.96   469.6 1755.97
   535.7  1767.9   565.6 1793.39   585.5 1802.17   595.5 1821.29   615.4 1823.69
     645 1858.55   664.5 1864.89   693.9    1901   723.2 1916.42   752.6 1949.05
   772.2 1951.41   791.7 1985.13   821.1 1997.77   850.4 2031.78   879.8 2047.75
#Mann= 3 , 0 , 0
       0      .1       0   454.6    .045       0   469.6      .1       0
Bank Sta=454.6,469.6
XS Rating Curve= 0 ,0
Exp/Cntr=0.3,0.1

Type RM Length L Ch R = 1 ,9431.3  ,191.1,190.9,190.6
XS GIS Cut Line= 4
     1757604.241       96472.119     1757484.839       96138.695
     1757475.828       95940.443     1757331.644       95609.271
#Sta/Elev= 30
       0 1972.16    49.2 1963.39   108.2 1932.58   127.9 1928.73   167.2 1901.31
   177.1 1888.18   196.8 1885.86   216.4 1868.76   236.1 1861.61   255.8 1841.37
   275.5 1835.48   285.3 1822.85     305    1820   324.6 1798.88   393.8 1758.94
   427.8 1751.86   433.5 1751.38   442.8  1751.5   512.9 1758.26   612.8 1801.35
   632.9 1820.76     653 1822.73     673 1855.48   693.1 1863.69   713.2 1887.94
   763.3 1903.83   813.5 1940.48   833.6 1945.77   853.6 1965.77   913.8  1984.3
#Mann= 3 , 0 , 0
       0      .1       0   427.8    .045       0   442.8      .1       0
Bank Sta=427.8,442.8
XS Rating Curve= 0 ,0
Exp/Cntr=0.3,0.1

Type RM Length L Ch R = 1 ,9240.4  ,174.9,174.7,174.5
XS GIS Cut Line= 4
     1757725.896       96442.831      1757674.08       96138.695
     1757662.816       95933.684     1757592.977       95595.754
#Sta/Elev= 30
       0 2016.98    29.9 2004.64    39.8 1987.24    59.7 1986.22    69.7 1967.91
    89.6  1959.8   109.5 1937.18   129.4 1934.24   139.3 1917.47   159.2 1914.49
   179.1 1893.73   228.9 1868.42   248.8 1847.58   337.8 1793.53   347.6 1777.94
   367.2 1775.67   386.7 1753.46   421.8 1743.46   425.8 1743.35   436.8 1744.31
   494.3 1752.48   582.8 1800.21   671.6 1822.41   740.6 1881.63   760.3 1910.74
   770.2 1910.74   789.9 1931.91   829.3 1953.66     849 1957.02   858.9 1970.95
#Mann= 3 , 0 , 0
       0      .1       0   421.8    .045       0   436.8      .1       0
Bank Sta=421.8,436.8
XS Rating Curve= 0 ,0
Exp/Cntr=0.3,0.1

Type RM Length L Ch R = 1 ,9065.8  ,136.3,136.5,136.8
XS GIS Cut Line= 4
     1757927.206       96436.713     1757845.298       96093.637
      1757831.78       95881.868     1757764.265       95537.687
#Sta/Elev= 30
       0 1978.29    20.2 1974.38    40.3 1951.09   161.2 1889.11   211.6 1853.96
   231.8 1852.57   241.9  1838.9     262 1837.17   312.4 1804.16   332.6 1803.02
   342.6 1790.22   413.4 1751.83   452.3 1741.53   463.9 1741.06   467.3 1741.65
   534.6 1751.19     605 1802.83     625 1826.91   635.1 1827.23   655.1 1853.84
   705.2 1881.85   725.3 1903.33   745.3 1908.99   755.3 1925.46   775.4 1928.51
   825.5 1970.63   845.5 1971.53   855.5 1987.55   875.6 1989.76   915.7 2013.69
#Mann= 3 , 0 , 0
       0      .1       0   452.3    .045       0   467.3      .1       0
Bank Sta=452.3,467.3
XS Rating Curve= 0 ,0
Exp/Cntr=0.3,0.1

Type RM Length L Ch R = 1 ,8929.2  ,338.5,340.2,341.8
XS GIS Cut Line= 4
     1757937.665       96388.763     1757975.964        96032.81
     1757964.699       95816.535     1757912.883       95579.984
#Sta/Elev= 30
       0 1954.79   159.1 1854.83     179 1851.87     189 1837.48   208.8 1834.56
   248.6 1811.31   258.6  1796.7   278.4  1796.7   288.4 1783.46   348.1 1761.13
     358 1749.78   423.1 1739.86   436.8  1739.3   438.1 1739.35   476.1 1742.11
   515.5 1760.66   564.7 1800.76   584.7 1804.28   594.8  1823.8   614.9 1831.05
   635.1 1860.84   655.3 1870.08   665.4 1892.99   685.6 1895.77   695.7 1916.19
   715.8  1923.3     736 1946.14   786.5 1971.12   806.6  1995.9   816.7 1997.49
#Mann= 3 , 0 , 0
       0      .1       0   423.1    .045       0   438.1      .1       0
Bank Sta=423.1,438.1
XS Rating Curve= 0 ,0
Exp/Cntr=0.3,0.1

Type RM Length L Ch R = 1 ,8589    ,156.8,149.2,141.7
XS GIS Cut Line= 4
     1758358.158       96475.966     1758295.438       96122.945
     1758299.075       95955.644     1758278.608       95539.703
#Sta/Elev= 30
       0    1805      10 1800.93    59.8  1796.3   109.6    1786   129.5 1784.45
   149.4 1778.96     239 1766.46     249 1762.69   268.9 1762.19   318.7 1754.07
   368.4 1759.06   388.1 1746.25   407.8 1740.84   417.6 1729.91   427.4 1726.39
   437.3 1726.38   444.7 1726.91   459.7  1727.5   525.9 1733.75     635  1736.9
   644.9 1739.09   654.8 1749.18   674.6 1751.26   694.4 1763.46   704.4 1763.73
   714.3 1768.65   724.2  1779.4     744 1779.42   753.9 1785.81   942.3 1796.03
#Mann= 3 , 0 , 0
       0      .1       0   444.7    .045       0   459.7      .1       0
Bank Sta=444.7,459.7
XS Rating Curve= 0 ,0
Exp/Cntr=0.3,0.1

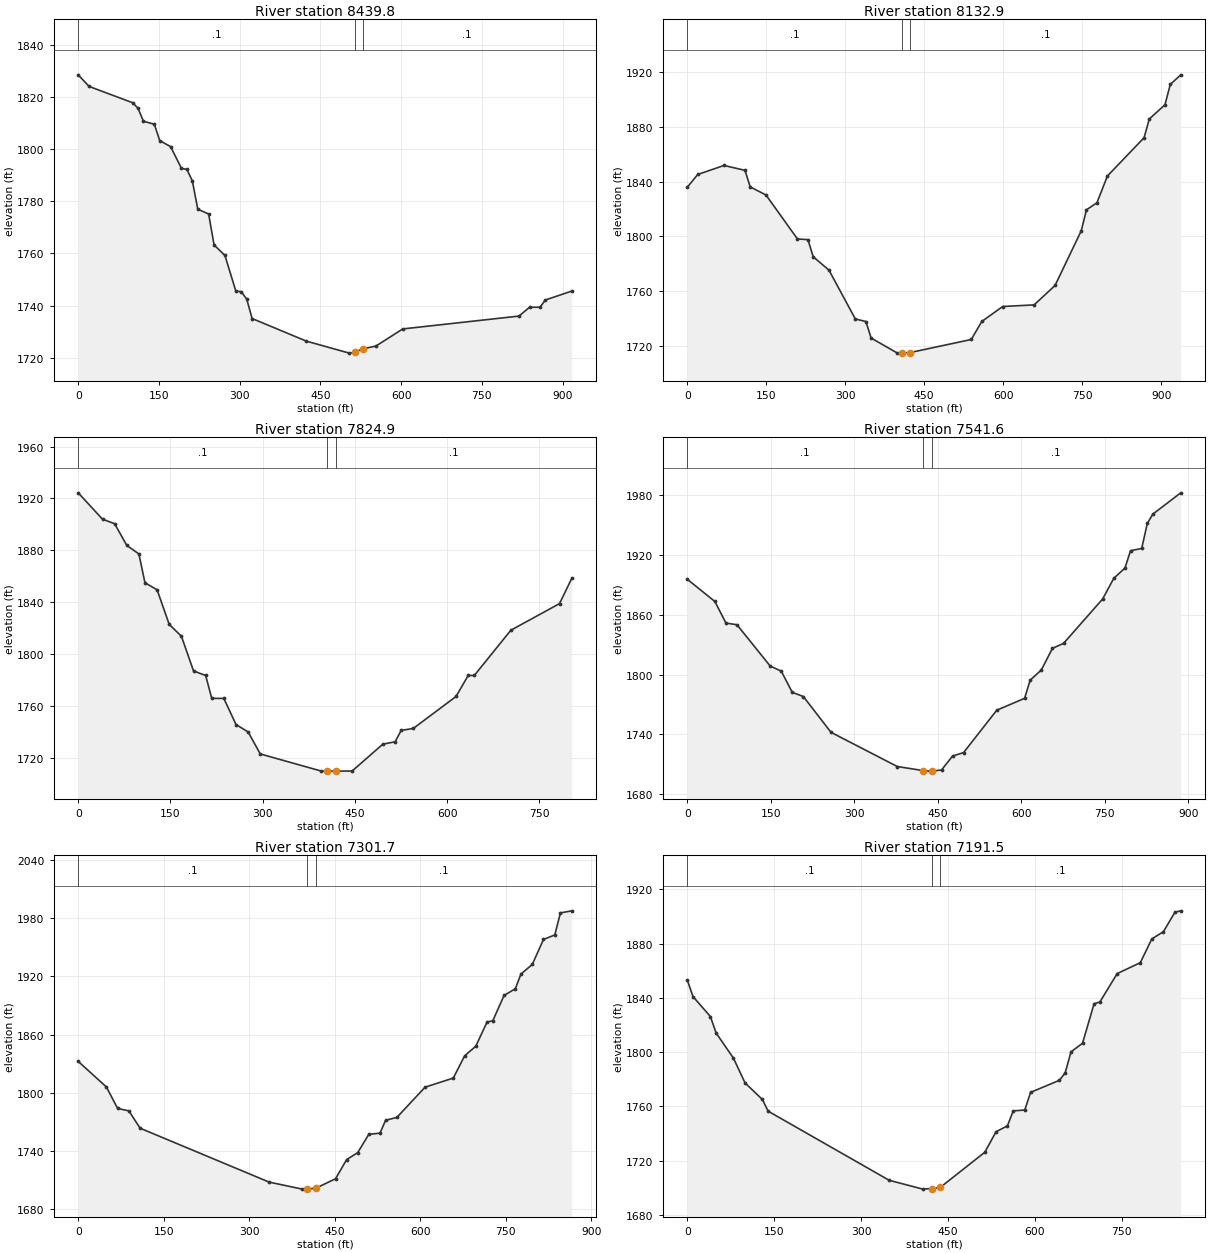
Type RM Length L Ch R = 1 ,8439.8  ,295.5,306.9,317.4
XS GIS Cut Line= 4
     1758454.782       96484.141     1758454.782       96049.978
     1758393.408        95861.31     1758400.228       95577.172
#Sta/Elev= 30
       0 1828.47    20.2 1824.02     101 1817.78   111.1 1815.66   121.2 1810.67
   141.4 1809.54   151.4 1803.25   171.6 1800.95   191.8 1792.63   201.9  1792.2
     212 1787.84   222.1 1776.97   242.3 1775.11   252.4 1763.27   272.6 1759.22
   292.8 1745.59   302.9 1745.33     313 1742.52   323.1 1735.05   424.1 1726.37
   503.6 1721.79   513.3 1722.08   528.3 1723.41   553.2 1724.51   602.8 1731.06
   818.8 1735.99   838.4 1739.36     858 1739.39   867.8 1742.15   916.8 1745.57
#Mann= 3 , 0 , 0
       0      .1       0   513.3    .045       0   528.3      .1       0
Bank Sta=513.3,528.3
XS Rating Curve= 0 ,0
Exp/Cntr=0.3,0.1

Type RM Length L Ch R = 1 ,8132.9  ,313.4,308.1,302.4
XS GIS Cut Line= 4
     1758486.606       96465.956     1758629.812       96250.011
     1758688.912       95965.873     1758897.414       95638.979
#Sta/Elev= 30
       0 1835.95    19.9 1845.32    69.8 1851.93   109.6 1848.35   119.6 1836.22
   149.5 1830.32   209.3 1798.13   229.2 1797.65   239.2  1785.1   269.1 1775.34
   319.2 1739.58   339.2 1737.73   349.2 1725.62   399.2 1714.59   408.2 1714.64
   423.2    1715   539.3 1724.57   559.3 1737.74     599 1748.71   658.7 1749.89
   698.5 1764.15   748.2 1804.15   758.1 1819.47     778 1824.63   797.9 1844.24
   867.5 1872.25   877.4 1885.93   907.2 1896.38   917.2 1911.18   937.1 1918.25
#Mann= 3 , 0 , 0
       0      .1       0   408.2    .045       0   423.2      .1       0
Bank Sta=408.2,423.2
XS Rating Curve= 0 ,0
Exp/Cntr=0.3,0.1

Type RM Length L Ch R = 1 ,7824.9  ,275.4,283.2,291.3
XS GIS Cut Line= 4
     1758868.488       96500.053     1758970.778       96190.911
     1758963.958       96011.335     1759011.694       95718.104
#Sta/Elev= 30
       0 1924.32    39.5 1903.99    59.2 1900.53    78.9 1883.82    98.7 1877.18
   108.5 1855.01   128.3 1849.53     148 1822.85   167.8 1813.77   187.5    1787
   207.2 1783.52   217.1 1765.92   236.8  1765.8   256.6  1745.7   276.3 1739.96
     296 1723.03   395.5 1709.78   404.4 1709.78   419.4 1709.79   445.4 1709.87
   495.4 1730.61   515.2 1732.37   525.1 1741.14   544.9 1742.71   614.3 1767.32
   634.1 1783.52     644 1783.52   703.4 1818.39   782.6 1838.92   802.4 1858.31
#Mann= 3 , 0 , 0
       0      .1       0   404.4    .045       0   419.4      .1       0
Bank Sta=404.4,419.4
XS Rating Curve= 0 ,0
Exp/Cntr=0.3,0.1

Type RM Length L Ch R = 1 ,7541.6  ,240.1,239.9,239.7
XS GIS Cut Line= 4
     1759063.975       96559.154        1759214.       96256.831
     1759284.191       96039.712     1759364.102       95729.341
#Sta/Elev= 30
       0 1895.78    49.6 1873.43    69.5 1851.74    89.3 1850.02   148.9 1808.56
   168.8 1803.39   188.6  1782.1   208.5 1777.89   258.1 1741.91   377.2 1707.52
   423.7 1703.43   436.7 1702.89   438.7 1702.96   456.6    1704   476.4 1718.04
   496.2 1721.52   555.8 1764.11   605.8 1776.08   615.8 1794.34   635.8 1804.52
   655.8  1826.3   675.8 1831.33     746 1875.98     766 1896.74     786 1907.02
     796 1924.42   816.1 1926.76   826.1 1951.83   836.1 1961.25   886.2 1982.65
#Mann= 3 , 0 , 0
       0      .1       0   423.7    .045       0   438.7      .1       0
Bank Sta=423.7,438.7
XS Rating Curve= 0 ,0
Exp/Cntr=0.3,0.1

Type RM Length L Ch R = 1 ,7301.7  ,110.5,110.2,109.9
XS GIS Cut Line= 4
     1759232.185       96570.519     1759427.672       96375.032
     1759500.411       96143.175     1759523.143       95797.663
#Sta/Elev= 30
       0 1832.38    49.4 1805.99    69.1 1783.86    88.9 1781.29   108.6 1763.42
   334.8 1707.83   393.1 1700.56   402.1 1700.62   417.1 1701.58   451.4 1711.28
   470.9 1731.04   490.3 1738.25   509.7 1757.03   529.4 1758.38   539.2 1771.56
     559 1774.58   608.5 1805.77     658 1815.17   677.8 1838.04   697.5 1848.09
   717.3 1873.12   727.2 1874.18     747 1900.39   766.8 1907.32   776.7 1922.54
   796.5 1932.38   816.2 1958.23     836 1962.83   845.9 1985.58   865.7 1987.73
#Mann= 3 , 0 , 0
       0      .1       0   402.1    .045       0   417.1      .1       0
Bank Sta=402.1,417.1
XS Rating Curve= 0 ,0
Exp/Cntr=0.3,0.1

Type RM Length L Ch R = 1 ,7191.5  ,171.4,166.6,161.9
XS GIS Cut Line= 4
     1759343.567       96638.713       1759543.6       96377.305
     1759604.974       96172.726     1759641.344       95865.856
#Sta/Elev= 30
       0 1853.19      10  1840.9    39.9 1826.25    49.9 1814.06    79.8  1795.5
    99.8 1777.28   129.7 1765.08   139.6 1756.48   348.6 1705.52   406.8 1699.02
   421.7 1699.48   436.7 1700.29   513.6  1726.2     533 1741.32   552.7 1745.67
   562.7 1756.69   582.6 1757.33   592.6 1770.34   642.4 1779.22   652.4 1784.76
   662.4 1800.22   682.3 1806.55   702.2 1835.63   712.2 1836.94   742.1 1857.89
     782 1865.92   801.9 1883.45   821.9 1888.76   841.8 1903.14   851.8 1904.14
#Mann= 3 , 0 , 0
       0      .1       0   421.7    .045       0   436.7      .1       0
Bank Sta=421.7,436.7
XS Rating Curve= 0 ,0
Exp/Cntr=0.3,0.1

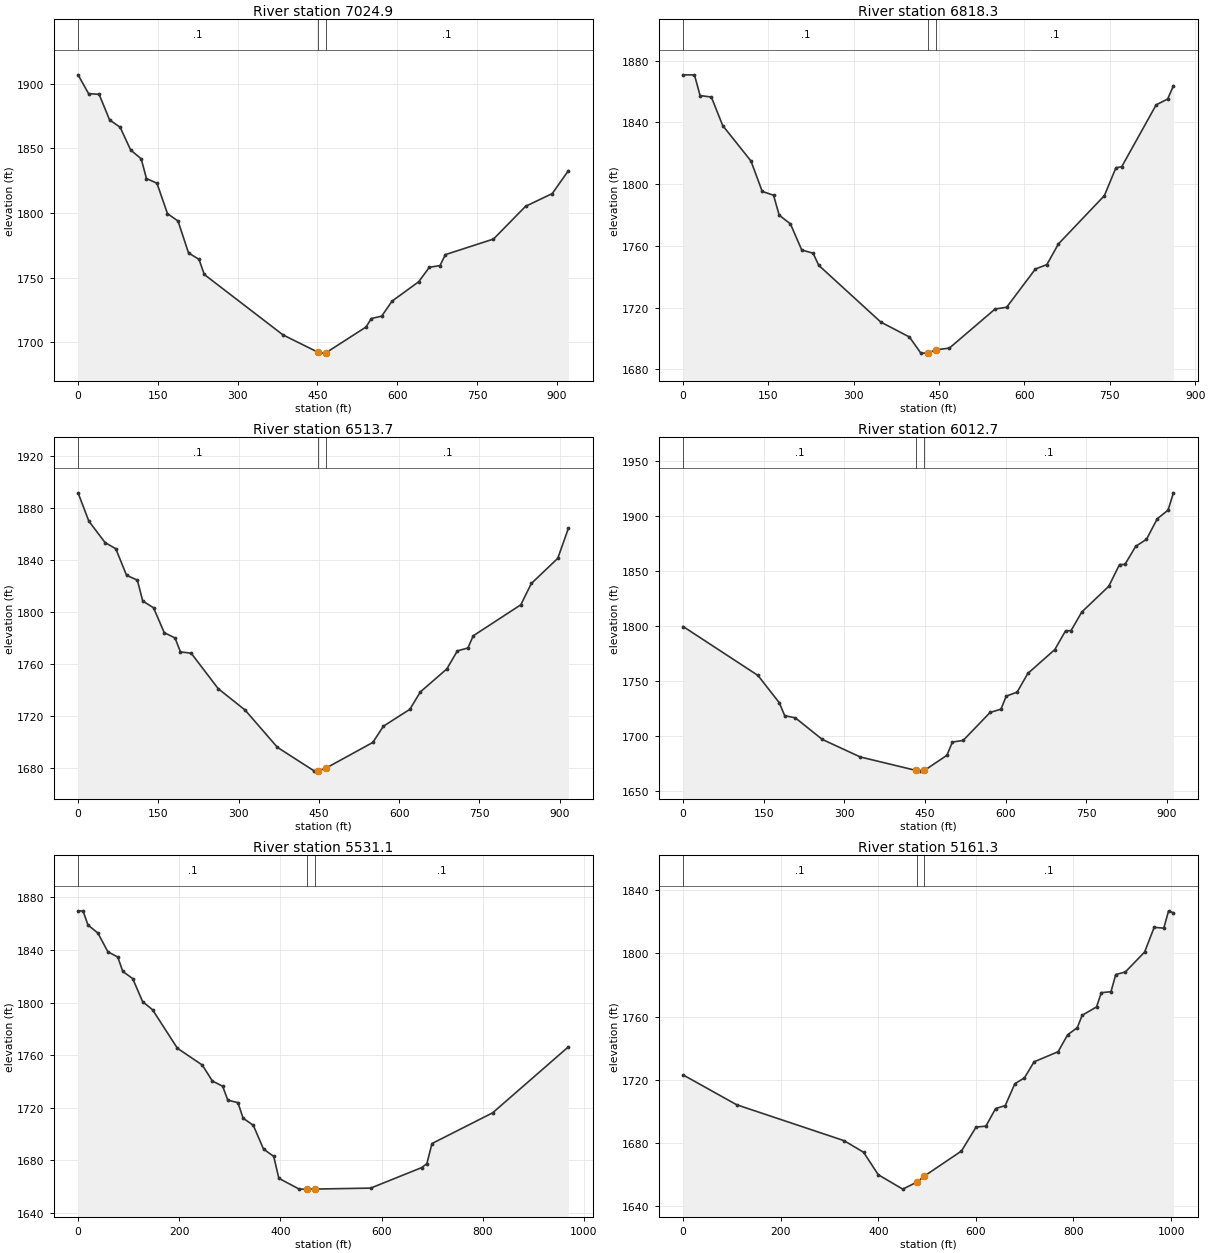
Type RM Length L Ch R = 1 ,7024.9  ,210.4,206.6,202.7
XS GIS Cut Line= 4
      1759577.34       96777.785     1759716.357       96450.045
     1759736.815       96206.822     1759843.362       95903.412
#Sta/Elev= 30
       0 1906.87    19.8 1892.31    39.6 1891.78    59.3 1871.98    79.1 1866.32
    98.9 1848.68   118.7 1841.86   128.6 1826.61   148.3 1822.98   168.1 1799.45
   187.9 1793.74   207.7    1769   227.4 1764.07   237.3 1752.36   385.3 1705.58
   450.7 1692.25   453.6 1691.48   465.7 1691.68   541.5 1711.73   551.3 1718.28
   570.8 1720.09   590.3 1731.73   640.3  1746.7   660.4  1757.9   680.5 1759.27
   690.5  1767.7     781 1779.78   841.3 1805.11   891.5 1814.98   921.7 1832.64
#Mann= 3 , 0 , 0
       0      .1       0   450.7    .045       0   465.7      .1       0
Bank Sta=450.7,465.7
XS Rating Curve= 0 ,0
Exp/Cntr=0.3,0.1

Type RM Length L Ch R = 1 ,6818.3  ,302.2,304.7,307.1
XS GIS Cut Line= 4
     1759841.377       96788.738     1759936.848       96454.591
     1759918.663       96254.558      1759982.31       95947.688
#Sta/Elev= 30
       0 1870.85    19.9 1870.79    29.8  1857.4    49.6 1856.45    69.5 1837.98
   119.2    1815     139 1795.27   158.9 1792.81   168.8  1779.9   188.6  1774.2
   208.5 1757.28   228.4 1755.26   238.3  1747.4   347.5 1710.57   397.7 1700.94
   417.8 1690.46   429.7 1690.51   444.7 1692.61     468 1693.73   548.4 1719.08
   568.6 1720.18   619.1 1744.96   639.4 1747.87   659.6 1761.23   740.5 1792.58
   760.7 1810.63   770.8 1811.21   831.4 1851.37   851.7 1855.18   861.8 1863.78
#Mann= 3 , 0 , 0
       0      .1       0   429.7    .045       0   444.7      .1       0
Bank Sta=429.7,444.7
XS Rating Curve= 0 ,0
Exp/Cntr=0.3,0.1

Type RM Length L Ch R = 1 ,6513.7  ,494.6,500.9,507.2
XS GIS Cut Line= 4
     1760133.831       96875.183     1760218.713       96522.784
     1760221.436       96324.645     1760293.785       95976.719
#Sta/Elev= 30
       0 1891.97    20.1 1870.24    50.3  1853.7    70.5 1848.88    90.6 1828.46
   110.8 1824.71   120.8 1808.67     141  1803.4   161.1 1784.24   181.2 1780.17
   191.3 1769.43   211.4 1768.41   261.8 1741.13   312.1 1724.61   372.4 1695.94
   441.7 1677.57   449.1  1677.8   464.1 1680.09   550.7 1699.67   570.5 1712.18
   619.9 1725.19   639.6 1738.62     689 1756.32   708.7 1770.22   728.4 1772.44
   738.3 1781.82   827.2 1805.72   846.9 1822.14   896.3 1841.53     916 1864.53
#Mann= 3 , 0 , 0
       0      .1       0   449.1    .045       0   464.1      .1       0
Bank Sta=449.1,464.1
XS Rating Curve= 0 ,0
Exp/Cntr=0.3,0.1

Type RM Length L Ch R = 1 ,6012.7  ,489.1,481.7,473.2
XS GIS Cut Line= 4
     1760611.999       96902.032     1760656.511       96667.658
     1760730.162       96415.948      1760781.79       96008.013
#Sta/Elev= 30
       0  1799.4   139.2 1754.98   178.9 1730.17   188.9 1718.46   208.7  1716.5
   258.7 1696.94   329.4 1681.01   433.6 1668.71   440.3 1668.13   448.6  1668.7
   490.7 1682.52   500.8 1694.51   520.9 1696.02     571 1721.41   591.1 1724.34
   601.1 1736.25   621.2 1739.83   641.2 1756.83   691.4  1778.5   711.4 1795.58
   721.5 1795.65   741.5 1812.54   791.7 1835.92   811.7 1855.66   821.8 1855.76
   841.8 1872.19   861.9 1878.56   881.9 1897.21     902 1905.02     912 1920.76
#Mann= 3 , 0 , 0
       0      .1       0   433.6    .045       0   448.6      .1       0
Bank Sta=433.6,448.6
XS Rating Curve= 0 ,0
Exp/Cntr=0.3,0.1

Type RM Length L Ch R = 1 ,5531.1  ,389.3,369.8,350.4
XS GIS Cut Line= 4
      1761132.37       97043.286     1761140.444       96797.867
     1761157.506       96313.658      1761113.84        96078.32
#Sta/Elev= 30
       0 1869.66     9.8 1869.76    19.6 1858.99    39.3 1852.82    58.9 1838.66
    78.6 1834.59    88.4  1823.7     108 1818.25   127.7 1800.66   147.3 1794.54
   196.4 1765.26   245.6 1752.49   265.7 1740.29   285.9 1736.38     296 1725.83
   316.2 1723.86   326.3 1712.09   346.5 1706.68   366.7 1688.57   386.9 1683.01
     397 1666.35   437.3 1658.11     453 1658.12     468 1658.16   578.6 1658.89
   679.6 1674.51   689.7 1677.52   699.8 1692.78   819.8 1716.16   969.4 1766.29
#Mann= 3 , 0 , 0
       0      .1       0     453    .045       0     468      .1       0
Bank Sta=453,468
XS Rating Curve= 0 ,0
Exp/Cntr=0.3,0.1

Type RM Length L Ch R = 1 ,5161.3  ,307.2,325.2,342.8
XS GIS Cut Line= 4
     1761704.895       96884.708     1761641.678       96643.259
     1761355.266       96377.305     1761238.905        96032.08
#Sta/Elev= 30
       0 1723.06   109.8 1704.15   329.8 1681.42   369.8 1674.09   399.9 1659.83
     450 1650.72   479.5 1655.22   494.5 1659.03   570.3 1674.84   600.4 1690.05
   620.4  1690.6   640.4 1701.76   660.1 1703.64   679.8 1717.49   699.5 1721.22
   719.2 1731.36   768.4 1737.77   788.1 1748.55   807.8    1753   817.7 1760.84
   847.2 1766.13     857 1775.19   876.8 1775.78   886.6 1786.66   906.3 1788.29
   945.7  1800.9   965.4 1816.57     985 1816.05   994.9 1827.02  1004.8 1825.76
#Mann= 3 , 0 , 0
       0      .1       0   479.5    .045       0   494.5      .1       0
Bank Sta=479.5,494.5
XS Rating Curve= 0 ,0
Exp/Cntr=0.3,0.1

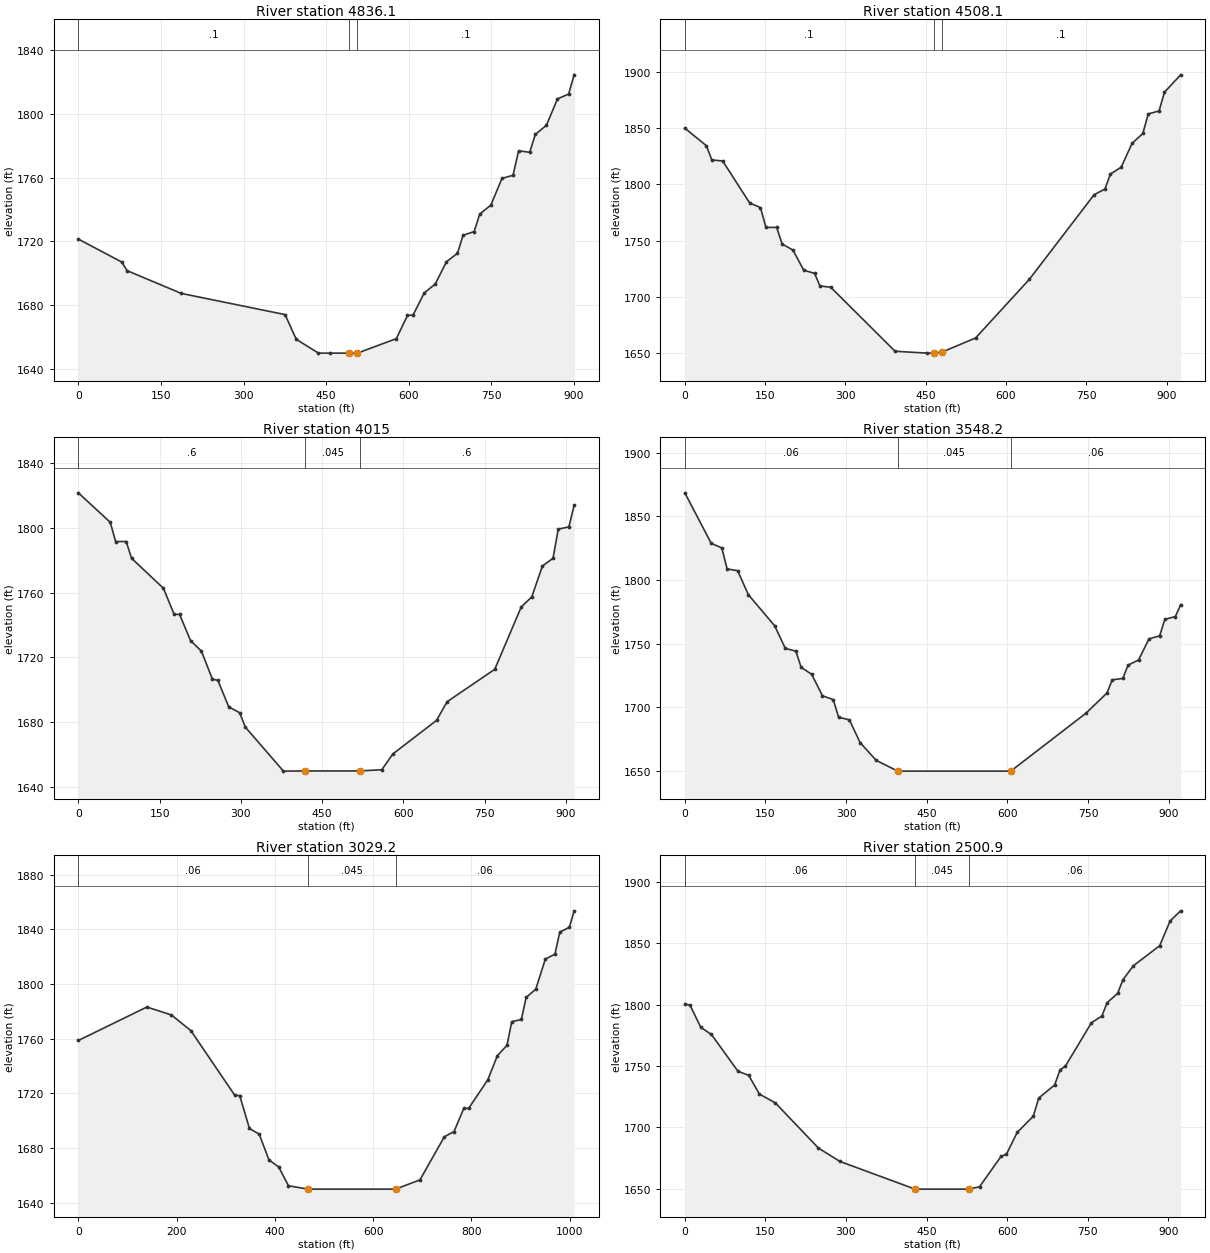
Type RM Length L Ch R = 1 ,4836.1  ,326.6,328,329.4
XS GIS Cut Line= 4
     1761721.237       96866.023     1761693.959       96552.335
     1761680.321       96209.095     1761628.039       95972.692
#Sta/Elev= 30
       0 1721.42    78.7 1707.02    88.6  1701.6     187  1687.3   375.5    1674
   395.7  1658.5   436.1 1649.81   456.3  1649.8   491.8  1649.8   506.8  1649.8
   577.6 1658.91   597.8 1673.48   607.9  1673.7   628.1 1687.52   648.3 1693.28
   668.5 1707.16   688.6  1712.5   698.7 1723.82   718.9 1726.17     729 1737.11
   749.2 1742.74   769.4 1759.54   789.5 1761.48   799.6 1776.85   819.8 1775.94
   829.9 1787.11   850.1 1792.88   870.2 1809.45   890.4  1812.5   900.5 1824.58
#Mann= 3 , 0 , 0
       0      .1       0   491.8    .045       0   506.8      .1       0
Bank Sta=491.8,506.8
XS Rating Curve= 0 ,0
Exp/Cntr=0.3,0.1

Type RM Length L Ch R = 1 ,4508.1  ,493.4,493.1,492.8
XS GIS Cut Line= 4
     1762017.917       96858.946     1761988.776       96618.338
     1761980.371        96227.28     1761926.922       95939.477
#Sta/Elev= 30
       0 1850.12    40.4 1834.44    50.5 1821.77    70.7  1820.9   121.2 1783.48
   141.4 1779.37   151.5 1761.75   171.7 1761.68   181.8 1746.96     202 1741.58
   222.2 1723.62   242.4 1720.82   252.4  1709.6   272.5 1708.49   392.8 1651.45
     453  1649.8   464.6  1649.8   479.6 1650.53   543.2 1663.29   643.6 1715.49
   764.7 1790.87   784.9 1795.91     795 1809.26   815.2 1815.34   835.4 1836.47
   855.6 1845.34   865.7 1862.74   885.9 1865.43     896 1882.06   926.2 1897.57
#Mann= 3 , 0 , 0
       0      .1       0   464.6    .045       0   479.6      .1       0
Bank Sta=464.6,479.6
XS Rating Curve= 0 ,0
Exp/Cntr=0.3,0.1

Type RM Length L Ch R = 1 ,4015    ,465.3,466.8,468.2
XS GIS Cut Line= 4
       1762425.9       96804.649     1762472.355       96634.073
      1762455.45       96149.995     1762402.943       95901.438
#Sta/Elev= 30
       0 1821.79    58.9 1803.57    68.8 1791.67    88.4 1791.67    98.2 1781.34
   157.2 1762.71   176.8 1746.63   186.9 1746.63   207.1  1730.4   227.2 1723.92
   247.4 1706.59   257.5 1705.83   277.7 1689.38   297.9 1685.77     308 1676.98
   378.6 1649.68     419  1649.8   519.9  1649.8   560.2 1650.55   580.4 1660.25
   661.2 1681.06   680.7 1692.61   768.6 1712.64   817.5 1751.18     837 1757.43
   856.6 1776.57   876.1 1781.26   885.9 1799.36   905.4  1800.7   915.2 1814.08
#Mann= 3 , 0 , 0
       0      .6       0     419    .045       0   519.9      .6       0
Bank Sta=419,519.9
XS Rating Curve= 0 ,0
Exp/Cntr=0.3,0.1

Type RM Length L Ch R = 1 ,3548.2  ,527.8,519.1,510
XS GIS Cut Line= 4
     1762855.517       96845.565     1762919.164       96618.255
     1762933.971       96118.134     1762928.033       95932.288
#Sta/Elev= 30
       0 1868.38    49.2 1828.69    68.8 1825.11    78.7 1808.63    98.4 1807.19
     118  1788.5   167.2 1763.94   186.9 1746.22   206.6 1744.04   216.4 1731.32
     236 1725.83   256.1 1708.97   276.1 1705.97   286.1 1692.13   306.1 1690.09
   326.1 1672.22   356.1 1658.23   396.2  1649.8   606.3  1649.8   746.2 1695.28
   785.3 1711.15   795.1 1721.48   814.7 1722.62   824.5 1733.03     844 1737.11
   863.6 1753.73   883.2    1756     893 1769.02   912.6 1771.24   922.3 1780.63
#Mann= 3 , 0 , 0
       0     .06       0   396.2    .045       0   606.3     .06       0
Bank Sta=396.2,606.3
XS Rating Curve= 0 ,0
Exp/Cntr=0.3,0.1

Type RM Length L Ch R = 1 ,3029.2  ,538.1,528.3,518.8
XS GIS Cut Line= 4
     1763535.176       96838.746     1763528.357       96550.061
     1763353.327       96086.348      1763353.15       95861.799
#Sta/Elev= 30
       0 1758.58   139.4 1783.06   189.2 1777.31     229 1765.81   318.5 1718.41
   328.4 1718.26   348.2  1694.2   368.1 1690.04   387.9 1671.21   407.7 1666.01
   427.6 1652.28   467.2  1649.8   645.6  1649.8   695.2 1656.57   744.8 1688.09
   764.6 1691.97   784.4 1708.87   794.2 1708.87   833.2 1729.79   852.8 1747.48
   872.3 1755.03     882 1772.32   901.6 1773.95   911.3 1790.14   930.9 1796.14
   950.4 1818.21   969.9 1821.76   979.7 1837.88   999.2 1841.44    1009 1853.48
#Mann= 3 , 0 , 0
       0     .06       0   467.2    .045       0   645.6     .06       0
Bank Sta=467.2,645.6
XS Rating Curve= 0 ,0
Exp/Cntr=0.3,0.1

Type RM Length L Ch R = 1 ,2500.9  ,473,468.7,464.3
XS GIS Cut Line= 4
     1764196.149       96340.931     1764072.689       96241.333
     1763703.386       95874.949     1763477.327        95782.65
#Sta/Elev= 30
       0 1800.61     9.9  1799.4    29.7  1781.5    49.6 1775.69    99.1 1745.72
     119 1742.44   138.8 1727.21   168.6 1719.98   248.7 1683.25   288.7 1672.35
   428.7  1649.8   528.8  1649.8   548.8 1651.78   588.8 1676.52   598.8 1678.24
   618.8 1695.98   648.8 1709.19   658.8  1723.9   688.6 1734.66   698.4 1746.84
   708.1 1749.67     757 1785.25   776.5 1790.75   786.3 1801.64   805.8 1809.21
   815.6 1820.29   835.1 1831.66     884 1847.97   903.5 1868.17     923 1876.36
#Mann= 3 , 0 , 0
       0     .06       0   428.7    .045       0   528.8     .06       0
Bank Sta=428.7,528.8
XS Rating Curve= 0 ,0
Exp/Cntr=0.3,0.1