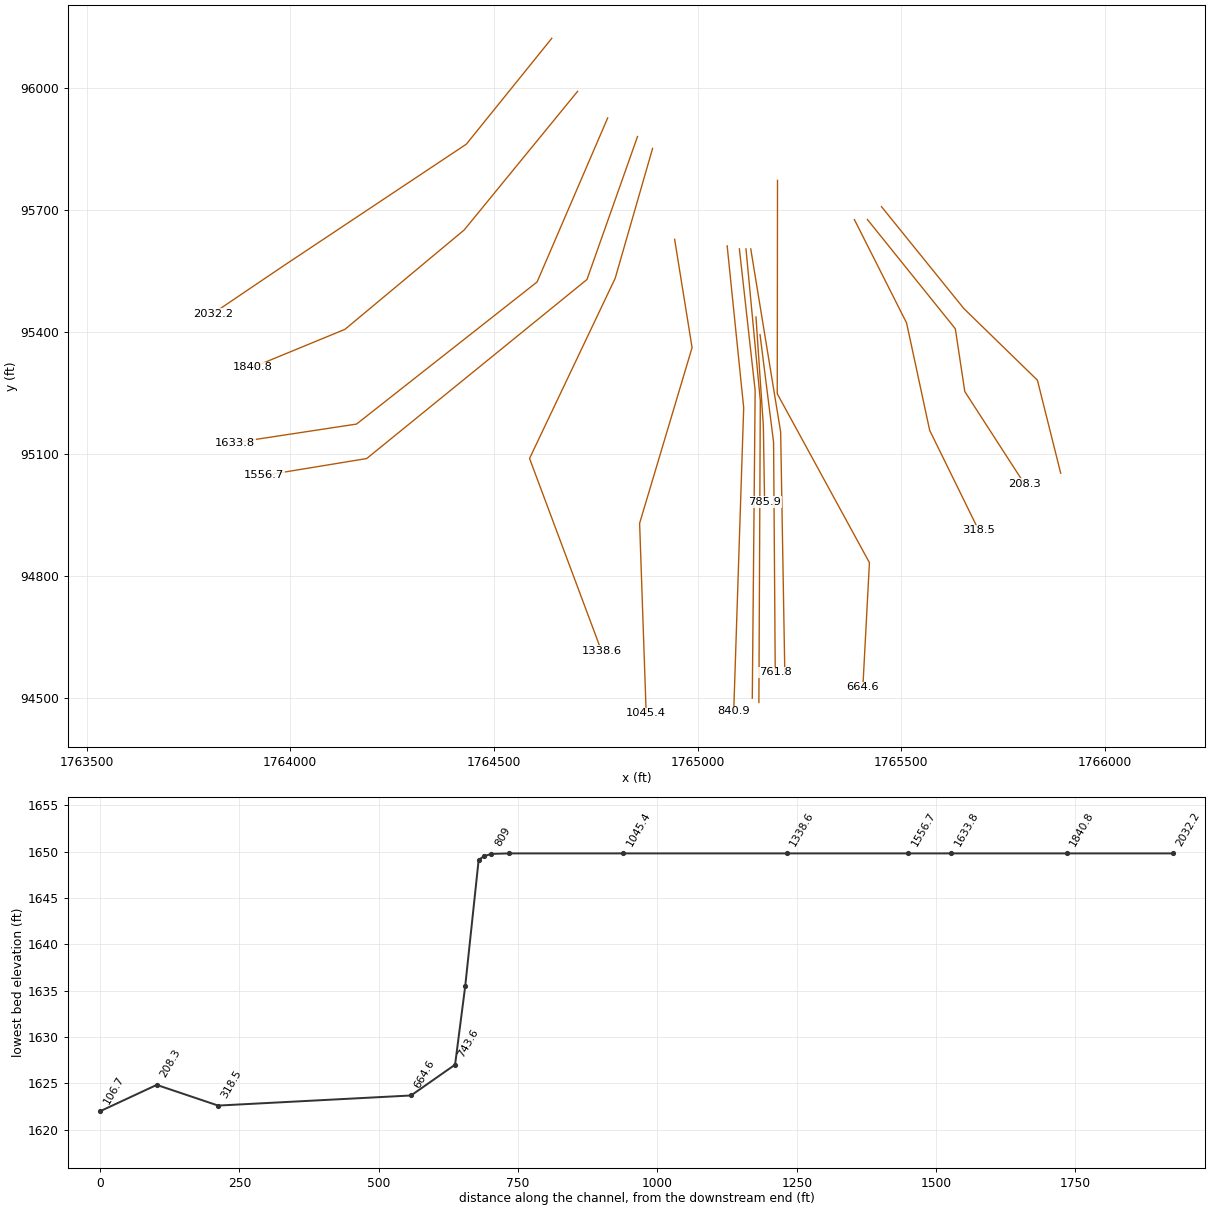
HEC-RAS study Big Branch A.prj: Big Branch A

--- Big Branch A.g01 (geometry) --- (continued)

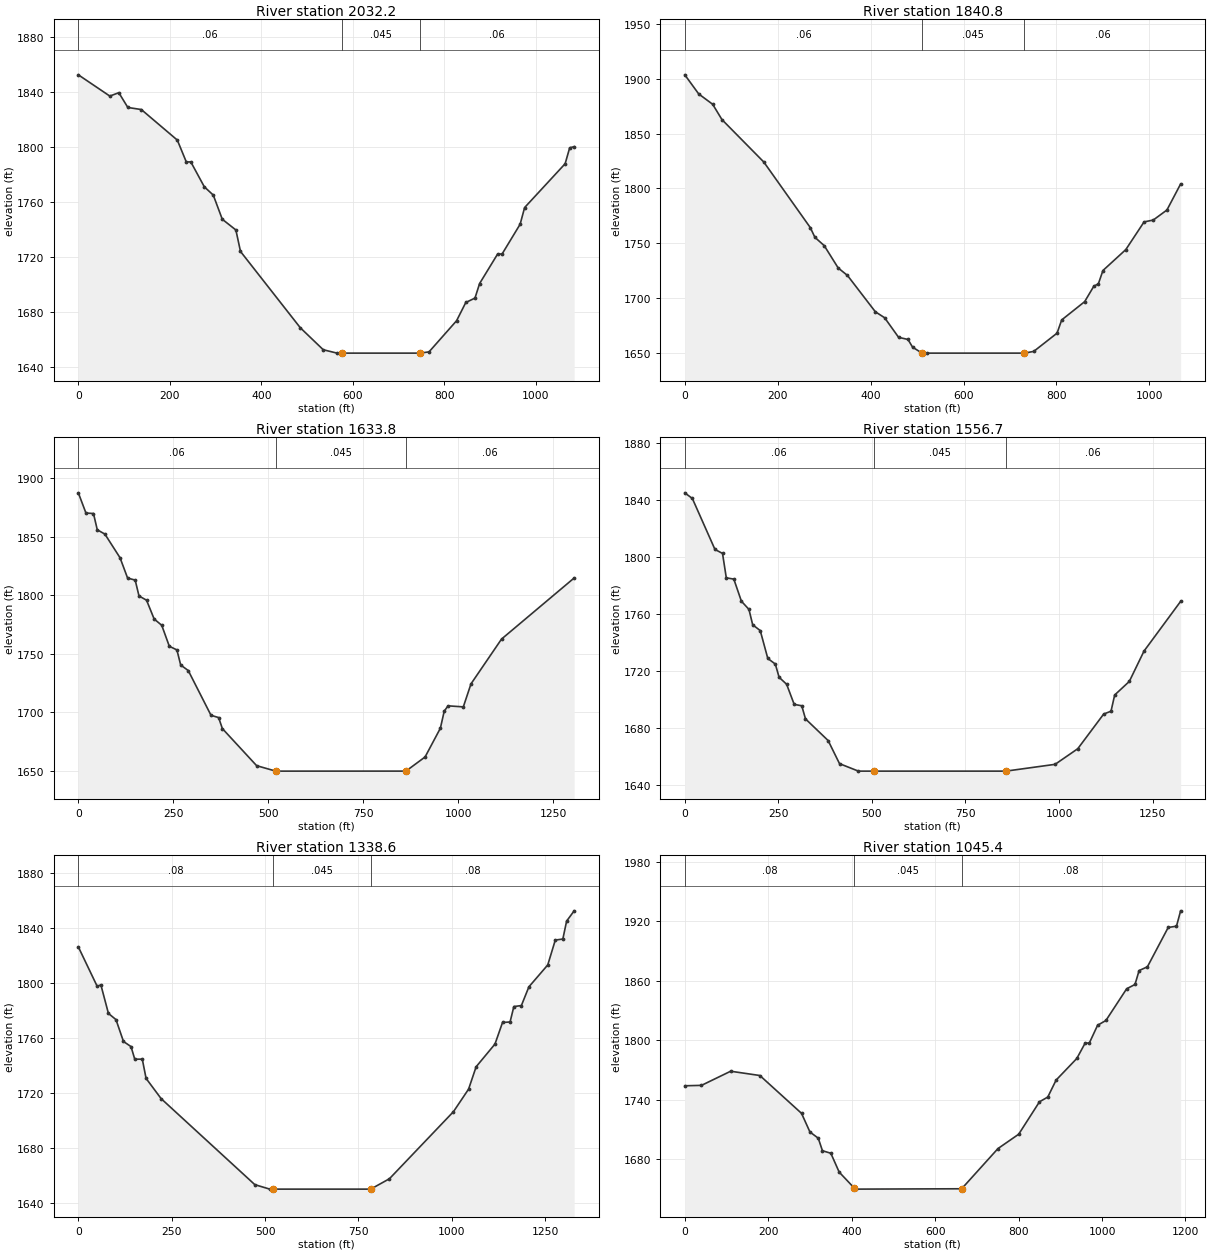
Type RM Length L Ch R = 1 ,2032.2  ,188.9,191.3,193.8
XS GIS Cut Line= 4
     1764642.179       96122.717     1764432.344       95862.369
     1763980.705        95561.26     1763809.582       95445.303
#Sta/Elev= 30
       0 1852.23    68.8 1836.78    88.5 1839.22   108.2 1828.49   137.7 1826.98
   216.4 1804.75     236 1788.88   245.9 1788.88   275.4 1770.79     295 1764.74
   314.7 1747.17   344.4 1739.38   354.5 1723.76   485.2 1668.27   535.4 1652.26
   565.6  1649.8   575.6  1649.8   746.5  1649.8   766.6  1650.7   826.9 1673.38
     847 1686.63   867.1 1689.84   877.2 1700.42   916.6  1721.9   926.4 1721.93
   965.8 1743.56   975.6 1755.68  1064.2 1787.58  1074.1 1799.13  1083.9 1799.97
#Mann= 3 , 0 , 0
       0     .06       0   575.6    .045       0   746.5     .06       0
Bank Sta=575.6,746.5
XS Rating Curve= 0 ,0
Exp/Cntr=0.3,0.1

Type RM Length L Ch R = 1 ,1840.8  ,207.6,207,206.4
XS GIS Cut Line= 4
     1764705.542       95992.298     1764427.086       95651.332
     1764134.424       95406.973     1763907.113       95313.207
#Sta/Elev= 30
       0 1903.56      30 1886.11      60 1876.71      80 1862.73   170.1 1824.04
   270.1  1764.3   280.1 1755.39   300.2 1747.79   330.2 1727.46   350.2 1720.62
   410.2 1687.51   430.2 1682.06   460.3 1664.18   480.4 1662.27   490.4 1655.22
   510.51649.859   520.5  1649.8   731.2 1649.81   751.2 1651.38   801.4 1668.02
   811.4 1680.08   860.8 1696.73   880.5  1710.8   890.3 1712.98   900.2 1725.14
   949.4 1744.21   988.7 1769.45  1008.4 1771.13  1037.9 1780.29  1067.4 1804.04
#Mann= 3 , 0 , 0
       0     .06       0   510.5    .045       0   731.2     .06       0
Bank Sta=510.5,731.2
XS Rating Curve= 0 ,0
Exp/Cntr=0.3,0.1

Type RM Length L Ch R = 1 ,1633.8  ,78,77.1,77.5
XS GIS Cut Line= 4
     1764779.418       95926.946     1764606.093        95523.47
     1764162.837       95173.979     1763864.492       95128.517
#Sta/Elev= 30
       0 1887.29      20 1870.07    39.9 1869.62    49.9 1855.72    69.9 1852.08
   109.8 1831.88   129.7 1814.56   149.7 1812.81   159.7 1799.29   179.6 1795.65
   199.6 1779.62   219.6 1774.26   239.5 1756.37   259.5 1753.23   269.5 1740.36
   289.4 1735.63   349.3 1697.44   369.3 1695.51   379.2 1686.11   469.4 1654.46
   519.8  1649.8   862.5 1649.82   912.9 1661.88   953.2 1686.43   963.3 1700.97
   973.4 1705.52  1013.6 1704.63  1033.8 1724.28  1114.2 1762.49  1305.4 1814.62
#Mann= 3 , 0 , 0
       0     .06       0   519.8    .045       0   862.5     .06       0
Bank Sta=519.8,862.5
XS Rating Curve= 0 ,0
Exp/Cntr=0.3,0.1

Type RM Length L Ch R = 1 ,1556.7  ,206.5,218.1,228.5
XS GIS Cut Line= 4
     1764852.666       95881.171     1764728.545       95529.496
     1764187.733       95089.162     1763936.536       95047.789
#Sta/Elev= 30
       0 1845.19    20.2 1841.21    80.6 1805.44   100.8 1802.65   110.9 1785.49
     131 1784.62   151.2 1769.12   171.4 1763.35   181.4 1752.54   201.6 1748.47
   221.8 1728.91   241.9 1724.96     252 1715.68   272.1 1710.79   292.3 1696.66
   312.5 1695.69   322.5 1686.48     383 1671.27   413.4 1655.05   463.9  1649.8
   504.3  1649.8   858.1  1649.8   989.5 1654.57  1050.1 1665.54  1119.3 1689.87
  1138.9 1691.87  1148.7 1703.25  1187.8 1712.78    1227 1734.05  1324.9 1768.97
#Mann= 3 , 0 , 0
       0     .06       0   504.3    .045       0   858.1     .06       0
Bank Sta=504.3,858.1
XS Rating Curve= 0 ,0
Exp/Cntr=0.3,0.1

Type RM Length L Ch R = 1 ,1338.6  ,289.5,293.2,296.9
XS GIS Cut Line= 4
     1764889.695       95852.024     1764797.819       95532.477
     1764587.596       95089.419     1764764.017       94616.451
#Sta/Elev= 30
       0 1826.14    50.4 1797.49    60.4 1798.46    80.6  1777.7   100.8 1773.21
   120.9 1757.28   141.1 1753.55   151.1 1744.39   171.3 1744.41   181.4 1730.41
   221.7 1715.68   472.6 1653.06   512.6  1649.8   522.6  1649.8   782.9  1649.8
     833 1657.34  1004.6 1706.23    1045 1722.59  1065.2 1738.87  1115.7 1755.43
  1135.9 1771.13  1156.1 1771.49  1166.2 1782.69  1186.4 1783.45  1206.5 1797.07
    1257    1813  1277.2 1831.12  1297.4 1831.87  1307.5 1844.92  1327.7  1852.4
#Mann= 3 , 0 , 0
       0     .08       0   522.6    .045       0   782.9     .08       0
Bank Sta=522.6,782.9
XS Rating Curve= 0 ,0
Exp/Cntr=0.3,0.1

Type RM Length L Ch R = 1 ,1045.4  ,198.8,204.6,210.3
XS GIS Cut Line= 4
     1764943.772       95628.372     1764986.592       95361.981
     1764857.802       94929.869     1764873.921       94462.409
#Sta/Elev= 30
       0 1754.08      40  1754.5   109.9 1768.76   179.9 1764.44   279.8 1726.27
   299.9 1707.49   319.9 1701.18   329.9 1688.54     350 1686.01     370 1666.99
   405.71651.094   410.1  1649.8   663.61650.162   750.6 1690.72   800.3 1705.21
   850.1 1737.93     870  1742.7   889.9  1759.8   939.6 1781.65   959.6 1797.21
   969.5 1797.17   989.4 1815.14  1009.3 1819.96  1059.1 1851.99    1079 1856.28
  1088.9 1870.34  1108.8 1874.13  1158.6 1913.81  1178.5 1915.12  1188.4 1930.61
#Mann= 3 , 0 , 0
       0     .08       0   405.7    .045       0   663.6     .08       0
Bank Sta=405.7,663.6
XS Rating Curve= 0 ,0
Exp/Cntr=0.3,0.1

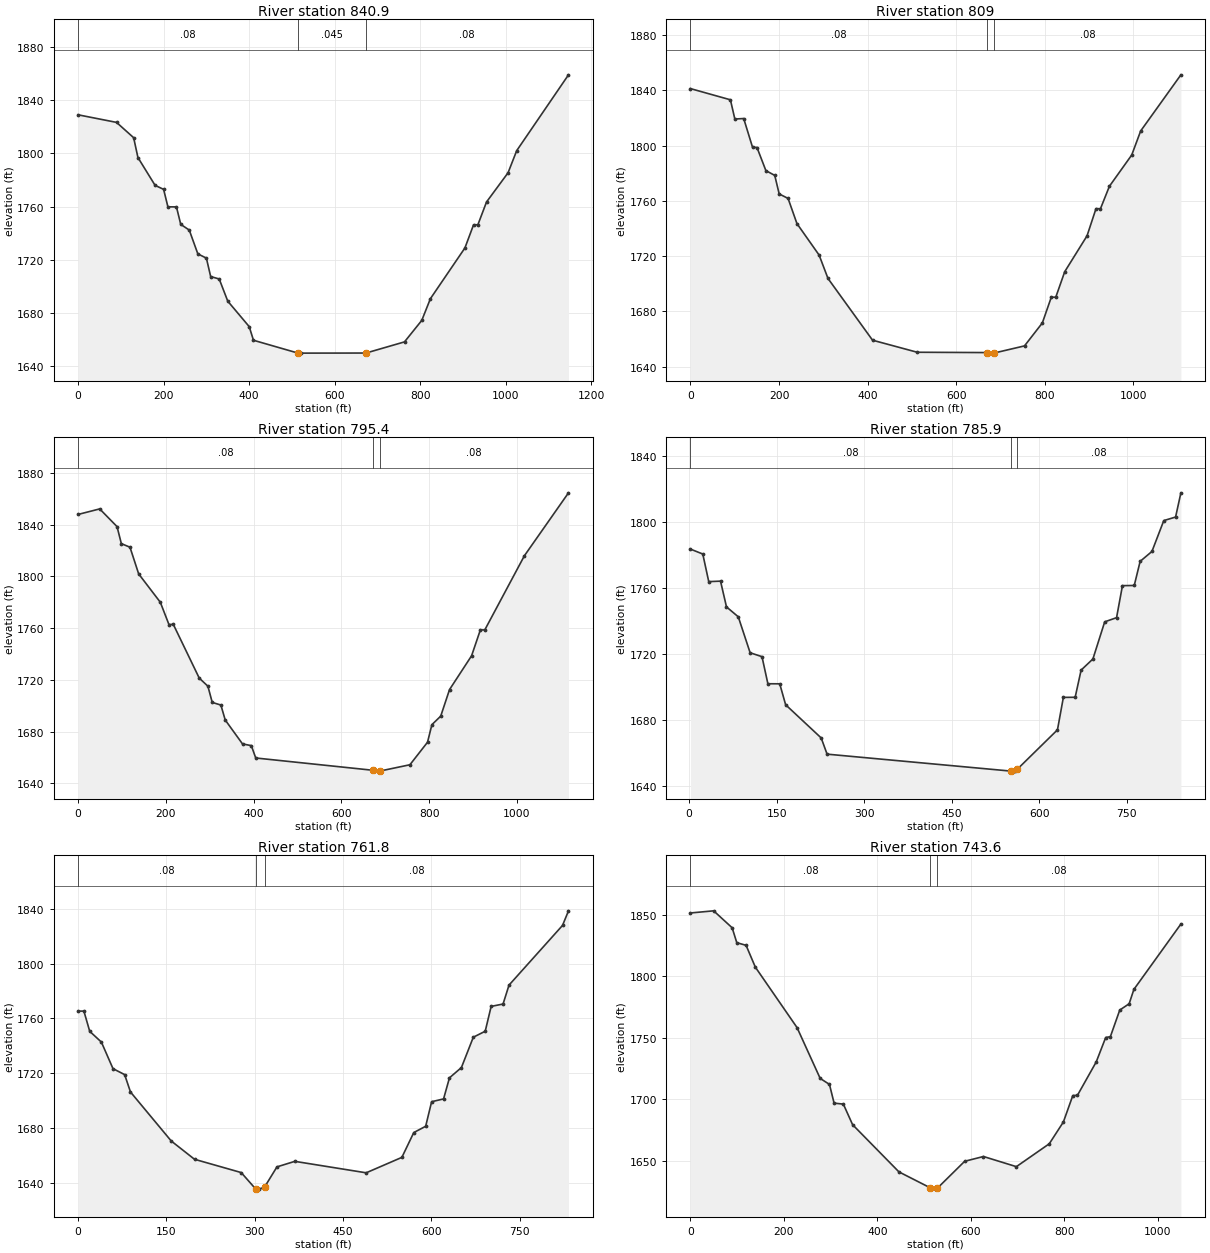
Type RM Length L Ch R = 1 ,840.9   ,31.2,31.9,32.6
XS GIS Cut Line= 3
     1765072.726       95612.253     1765113.294       95214.162
     1765088.845       94467.782
#Sta/Elev= 30
       0 1829.08      90 1823.37     130 1811.84     140 1796.94   180.1 1776.03
   200.1 1772.98   210.1 1759.85   230.1  1759.8   240.1 1746.67   260.1 1742.34
   280.1 1724.46   300.1 1721.26   310.1 1707.42   330.1 1705.56   350.1 1688.88
   400.2 1669.75   410.2 1659.48   514.51649.807   521.2  1649.8   673.31649.867
   763.4 1658.26   803.8 1674.43     824 1690.77   904.7 1728.92   924.9 1746.35
     935 1746.35   955.2 1763.48  1005.6 1785.49  1025.8 1802.11  1146.9 1859.15
#Mann= 3 , 0 , 0
       0     .08       0   514.5    .045       0   673.3     .08       0
Bank Sta=514.5,673.3
XS Rating Curve= 0 ,0
Exp/Cntr=0.3,0.1

Type RM Length L Ch R = 1 ,809     ,13.4,13.5,13.6
XS GIS Cut Line= 3
     1765102.736       95604.827      1765141.45       95256.396
     1765134.411       94499.704
#Sta/Elev= 30
       0 1841.31    90.2  1833.2   100.2 1819.29   120.2 1819.64   140.2 1798.78
   150.2 1798.66   170.3 1781.91   190.3 1778.46   200.3 1765.04   220.4 1761.78
   240.4 1743.56   290.5 1720.74   310.5 1703.82   411.1 1659.12     512 1650.38
   669.81650.148   683.5 1649.75   684.81649.758   754.2 1654.99   794.5 1671.62
   814.7 1690.25   824.8 1690.24     845 1708.72   895.4  1734.7   915.6 1754.37
   925.7 1754.32   945.9 1770.59   996.3 1793.23  1016.5 1810.65  1107.3 1851.29
#Mann= 3 , 0 , 0
       0     .08       0   669.8    .045       0   684.8     .08       0
Bank Sta=669.8,684.8
XS Rating Curve= 0 ,0
Exp/Cntr=0.3,0.1

Type RM Length L Ch R = 1 ,795.4   ,9,9.5,10
XS GIS Cut Line= 3
     1765118.911       95604.827     1765154.106        95231.76
     1765150.587       94489.145
#Sta/Elev= 30
       0 1847.77    49.3 1852.05    88.8 1838.38    98.6 1825.24   118.3 1822.45
   138.1 1801.84   187.4 1779.95   207.1  1762.7     217 1762.87   276.1 1721.35
   295.8 1715.11   305.7 1702.58   325.4 1700.54   335.3    1689   374.7 1670.51
   394.8  1669.2   404.8 1659.65   671.91650.158   685.8  1649.5   686.91649.502
   756.1 1654.42   796.2 1671.82   806.2 1685.39   826.3 1691.98   846.4 1712.52
   896.6 1738.59   916.6 1758.58   926.7 1758.58    1017  1815.9  1117.4 1864.47
#Mann= 3 , 0 , 0
       0     .08       0   671.9    .045       0   686.9     .08       0
Bank Sta=671.9,686.9
XS Rating Curve= 0 ,0
Exp/Cntr=0.3,0.1

Type RM Length L Ch R = 1 ,785.9   ,24.3,24.1,23.9
XS GIS Cut Line= 3
     1765143.477       95437.364     1765161.561        95169.74
     1765164.606       94982.284
#Sta/Elev= 30
     2.5 1783.67    23.6 1780.69    33.8 1763.96      54 1764.25    64.2 1748.64
    84.4 1742.63   104.7 1720.84     125 1718.48   135.1 1702.06   155.4 1702.02
   165.5 1689.33   226.4 1669.21   236.5 1659.39   551.2 1649.12   558.7  1649.1
   561.9 1650.11   631.1 1674.13   641.2 1693.79   661.4 1693.86   671.6 1710.33
   691.8 1717.08     712 1739.59   732.3 1742.11   742.4 1761.52   762.6 1761.62
   772.7 1776.23   792.9 1782.25   813.2 1800.96   833.4  1803.1   842.5 1817.78
#Mann= 3 , 0 , 0
     2.5     .08       0   551.2    .045       0   561.9     .08       0
Bank Sta=551.2,561.9
XS Rating Curve= 0 ,0
Exp/Cntr=0.3,0.1

Type RM Length L Ch R = 1 ,761.8   ,18,18.2,18.5
XS GIS Cut Line= 3
      1765153.45        95393.88     1765186.691       95129.024
     1765190.771       94563.254
#Sta/Elev= 30
       0 1765.32     9.9 1765.32    19.8 1750.58    39.6 1742.73    59.3 1723.36
    79.1    1719      89 1706.35   158.2  1670.6   197.7 1657.27     277 1647.58
   301.71635.544   307.4  1635.5   316.71637.028   337.7 1651.72     368 1655.76
   489.2  1647.4   549.8 1658.66     570 1676.75   590.2 1681.33   600.3 1699.24
   620.6 1701.29   630.6 1716.66   650.9 1724.16   671.1 1746.29   691.3 1750.63
   701.4 1768.76   721.6 1770.48   731.7 1784.27   822.6 1827.82   832.7 1838.45
#Mann= 3 , 0 , 0
       0     .08       0   301.7    .045       0   316.7     .08       0
Bank Sta=301.7,316.7
XS Rating Curve= 0 ,0
Exp/Cntr=0.3,0.1

Type RM Length L Ch R = 1 ,743.6   ,67.3,79,90.7
XS GIS Cut Line= 3
      1765130.69       95604.607     1765204.041       95154.587
     1765214.272       94561.378
#Sta/Elev= 30
       0 1851.45    49.6 1853.19    89.2 1839.41    99.1 1827.31     119 1825.15
   138.8 1807.43     228 1758.32   277.5 1717.02   297.4 1712.12   307.3  1696.9
   327.1 1696.12   346.9 1679.39     446 1641.04     5131628.102   526.4 1627.02
     5281627.672   586.7 1649.65   626.9 1653.53   697.3 1645.28   767.7 1663.88
   797.9  1681.6     818 1703.03     828 1703.29   868.2 1730.43   888.4 1750.24
   898.4  1750.9   918.5 1772.55   938.6 1777.67   948.7 1789.32  1049.3 1842.44
#Mann= 3 , 0 , 0
       0     .08       0     513    .045       0     528     .08       0
Bank Sta=513,528
XS Rating Curve= 0 ,0
Exp/Cntr=0.3,0.1

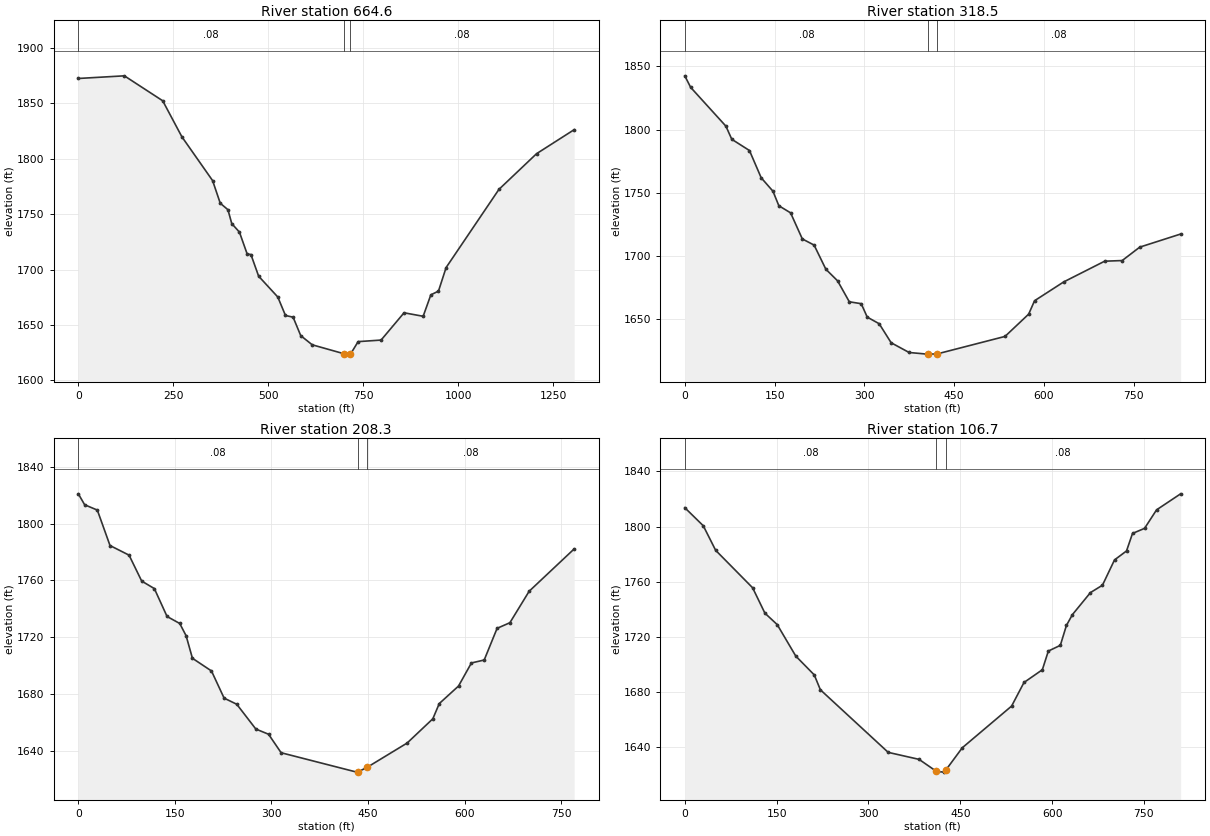
Type RM Length L Ch R = 1 ,664.6   ,352.6,346.1,339.2
XS GIS Cut Line= 4
     1765196.307       95773.446     1765195.698       95248.609
     1765421.978       94833.153     1765405.858       94526.886
#Sta/Elev= 30
       0 1872.59   121.1 1874.98     222 1852.45   272.5 1819.91   353.3 1780.37
   373.4 1759.95   393.6  1754.1   403.7 1741.57   423.9 1733.85   444.1 1714.24
   454.2 1713.57   474.4 1694.07   524.8 1675.28     545  1658.6   565.1 1657.06
   585.2 1640.39   615.4 1632.12   699.2 1624.02   714.2 1623.71   716.1  1623.7
   736.2 1634.99   796.6 1636.39     857 1661.03   907.3 1657.87   927.5 1677.22
   947.6  1680.6   967.7 1701.88  1106.7 1772.46  1205.7 1804.68  1304.6 1826.36
#Mann= 3 , 0 , 0
       0     .08       0   699.2    .045       0   714.2     .08       0
Bank Sta=699.2,714.2
XS Rating Curve= 0 ,0
Exp/Cntr=0.3,0.1

Type RM Length L Ch R = 1 ,318.5   ,111.7,110.2,108.7
XS GIS Cut Line= 4
     1765385.092       95676.903     1765513.197       95422.693
     1765569.905       95158.493     1765690.107       94913.001
#Sta/Elev= 30
       0  1842.6     9.8 1833.48    68.7 1802.79    78.5 1792.43     108 1783.56
   127.6 1762.01   147.2 1751.42   157.1  1739.9   176.7 1734.29   196.3 1713.66
     216  1708.8   235.6 1689.73   255.2 1680.55   274.8 1663.98   294.7 1662.48
   304.7 1651.88   324.7 1646.63   344.7 1631.59   374.7  1623.9   404.8 1622.61
   406.1 1622.61   421.1 1622.73   534.9 1636.61   574.4 1654.24   584.2 1664.81
     633 1679.71   701.3 1696.07   730.6 1696.58   759.9 1707.18   828.2 1717.54
#Mann= 3 , 0 , 0
       0     .08       0   406.1    .045       0   421.1     .08       0
Bank Sta=406.1,421.1
XS Rating Curve= 0 ,0
Exp/Cntr=0.3,0.1

Type RM Length L Ch R = 1 ,208.3   ,86.6,101.6,116.6
XS GIS Cut Line= 4
     1765417.072       95677.073     1765632.843       95408.417
     1765656.112       95253.993     1765802.075       95027.646
#Sta/Elev= 30
       0 1821.01     9.8 1813.31    29.5 1809.55    49.2 1784.56    78.8 1777.78
    98.4 1759.52   118.1  1754.2   137.8 1734.56   157.5 1729.62   167.4 1720.97
   177.2  1705.1   206.8 1696.15   226.4 1677.01   246.1 1672.67   275.7 1655.21
   295.4 1651.56     315  1638.5   432.4 1624.84   433.91624.894   448.91628.319
   510.7 1645.35   550.6 1662.44   560.6 1673.17   590.5 1685.52   610.5 1701.78
   630.4 1703.88   650.4  1726.2   670.3 1730.16   700.2 1752.34   770.1 1782.17
#Mann= 3 , 0 , 0
       0     .08       0   433.9    .045       0   448.9     .08       0
Bank Sta=433.9,448.9
XS Rating Curve= 0 ,0
Exp/Cntr=0.3,0.1

Type RM Length L Ch R = 1 ,106.7   ,111.7,106.7,101.7
XS GIS Cut Line= 4
     1765451.606       95708.652     1765653.977       95457.888
     1765834.352       95281.913     1765891.544       95053.145
#Sta/Elev= 30
       0 1813.67    30.2 1800.56    50.4 1782.78   110.8 1755.61   130.9 1737.21
     151 1728.92   181.3 1706.12   211.5 1692.47   221.5 1681.68   332.3 1636.32
   382.7 1631.25     411 1622.57     423    1622     426 1623.24   453.3 1639.65
   533.9 1669.88   554.1 1686.97   584.1 1696.21   593.9 1709.75   613.5 1713.91
   623.4 1728.28   633.2 1736.15   662.7 1752.14   682.3 1757.48     702 1775.82
   721.6 1782.31   731.4    1795   751.1  1798.7   770.7  1812.1     810 1823.72
#Mann= 3 , 0 , 0
       0     .08       0     411    .045       0     426     .08       0
Bank Sta=411,426
XS Rating Curve= 0 ,0
Exp/Cntr=0.3,0.1

Chan Stop Cuts=-1
Use User Specified Reach Order=0